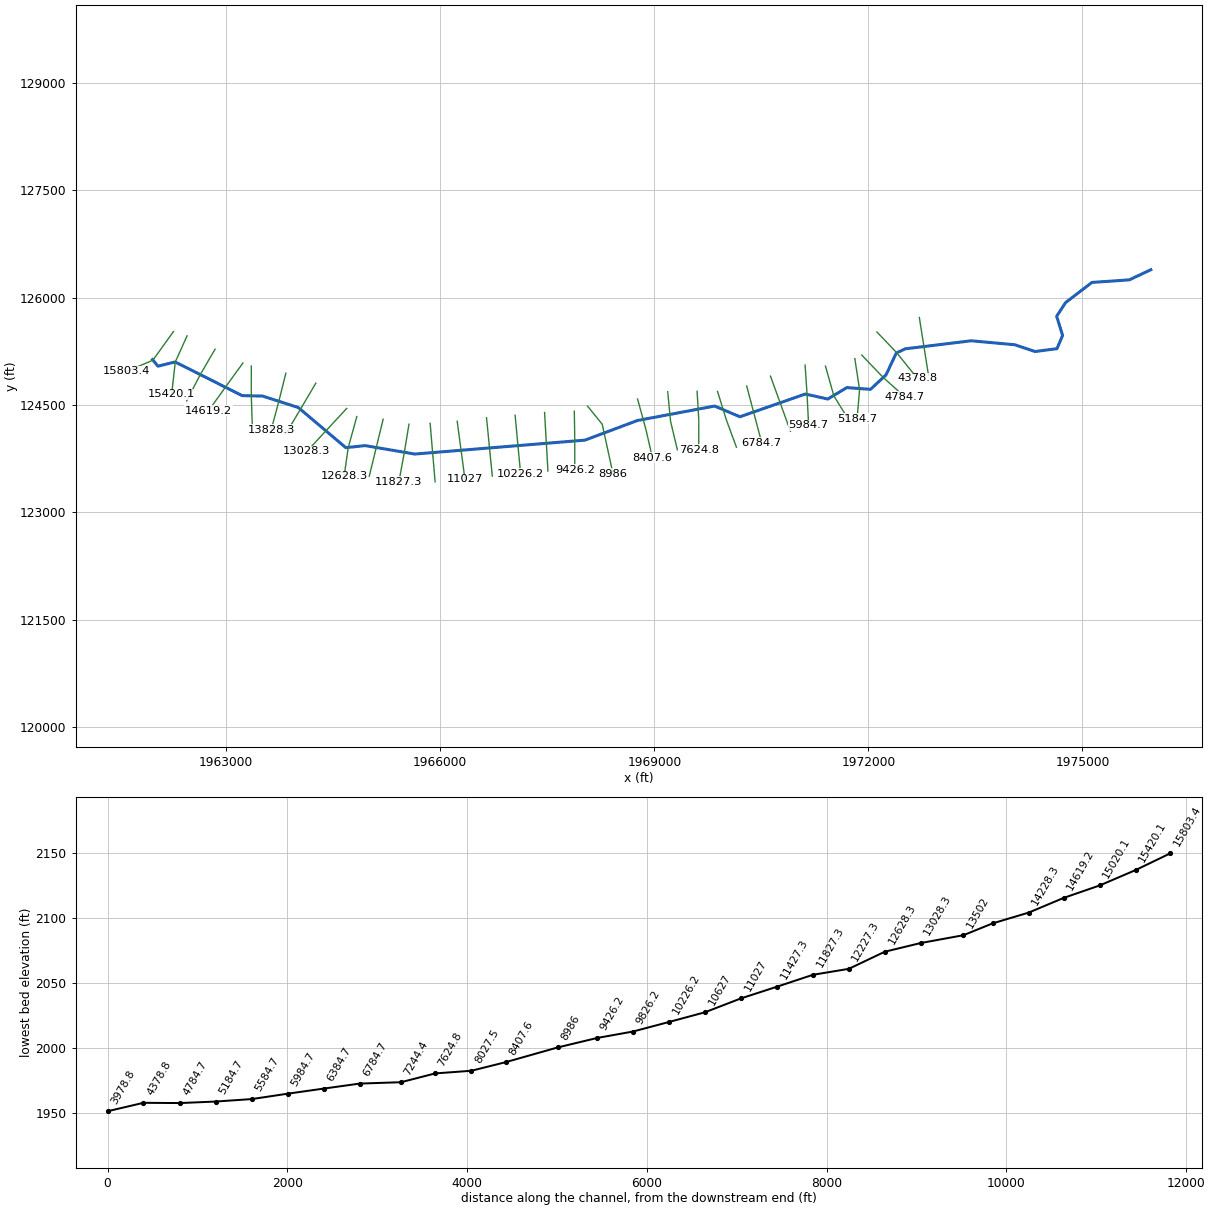
--- FvmlCrk.prj (project) ---

Proj Title=FvmlCrk
Current Plan=p01
Default Exp/Contr=0,0
English Units
Geom File=g01
Flow File=f01
Plan File=p01
BEGIN DESCRIPTION:
END DESCRIPTION:
DSS Export Rating Curves= 0
DSS Export Rating Curve Sorted= 0
DSS Export Volume Flow Curves= 0
DXF OffsetX= 0
DXF OffsetY= 0
DXF ScaleX= 0
DXF ScaleY= 0

--- FvmlCrk.p01 (plan) ---

Plan Title=Floodplain
Program Version=4.00
Geom File=g01
Flow File=f01
K Sum by GR=0
Std Step Tol=0.01
Critical Tol=0.01
Num of Std Step Trials=20
Max Error Tol=0.3
Flow Tol Ratio=0.001
Split Flow NTrial=30
Split Flow Tol=0.02
Split Flow Ratio=0.02
Log Output Level=0
Friction Slope Method=1
Unsteady Friction Slope Method=2
Unsteady Bridges Friction Slope Method=1
Global Log Level=0
CheckData=False
Run HTab=0
Run UNet=0
Run PostProcess=0
UNET Theta=0
UNET Theta Warmup=0
UNET ZTol=0
UNET ZSATol=0
UNET MxIter=0
UNET MaxInSteps=0
UNET DtIC=0
UNET DtMin=0
UNET MaxCRTS=0
UNET WFStab=0
UNET SFStab=0
UNET WFX=0
UNET SFX=0
UNET DSS MLevel=0
UNET DZMax Abort=0
UNET Convert EG Bridges=0
UNET Use Existing IB Tables=0
UNET Froude Limit=0
UNET Froude Power=0
Write IC File=0
Echo Input=False
Echo Output=False
Write Detailed=0

--- FvmlCrk.f01 (steady flow) ---

Flow Title=NFF Regression Equation
Program Version=4.00
Number of Profiles=1
Profile Names=P100yr
River Rch & RM=FvmlCrk,Main      ,15803.4
588.3161
River Rch & RM=FvmlCrk,Main      ,13502
622.1239
River Rch & RM=FvmlCrk,Main      ,13028.3
773.7824
River Rch & RM=FvmlCrk,Main      ,12227.3
834.9060
River Rch & RM=FvmlCrk,Main      ,10226.2
873.2227
River Rch & RM=FvmlCrk,Main      ,8986
968.1346
River Rch & RM=FvmlCrk,Main      ,5984.7
1071.128
River Rch & RM=FvmlCrk,Main      ,2682.1
1188.528
River Rch & RM=FvmlCrk,Main      ,159.9
    1211
Boundary for River Rch & Prof#=FvmlCrk,Main      ,1
Up Type=0
Dn Type=3
Dn Slope=0.029159

--- FvmlCrk.g01 (geometry) ---

Geom Title=USGS 3m DEM
Program Version=4.10

River Reach=FvmlCrk         ,Main
Reach XY= 30
     1961968.072      125135.174     1962044.356      125043.332
     1962284.412      125102.578     1963223.687       124632.44
     1963510.974      124626.016     1964010.974      124465.859
     1964676.339      123905.963     1964948.459      123933.878
     1965642.485       123816.12     1968027.871       124010.48
     1968764.238      124284.984     1969845.532      124486.826
     1970198.926      124336.969     1971116.443      124654.661
     1971430.245      124584.349     1971697.172      124744.505
     1972029.203      124719.766     1972246.652      124921.589
     1972391.183      125227.578     1972517.533      125286.331
     1973440.092      125398.468     1974050.992      125343.018
     1974335.882      125248.413     1974642.273       125288.19
     1974721.827        125473.1     1974637.973      125740.789
     1974763.754      125932.149      1975132.51      126213.697
     1975656.051       126249.29     1975958.142      126391.198

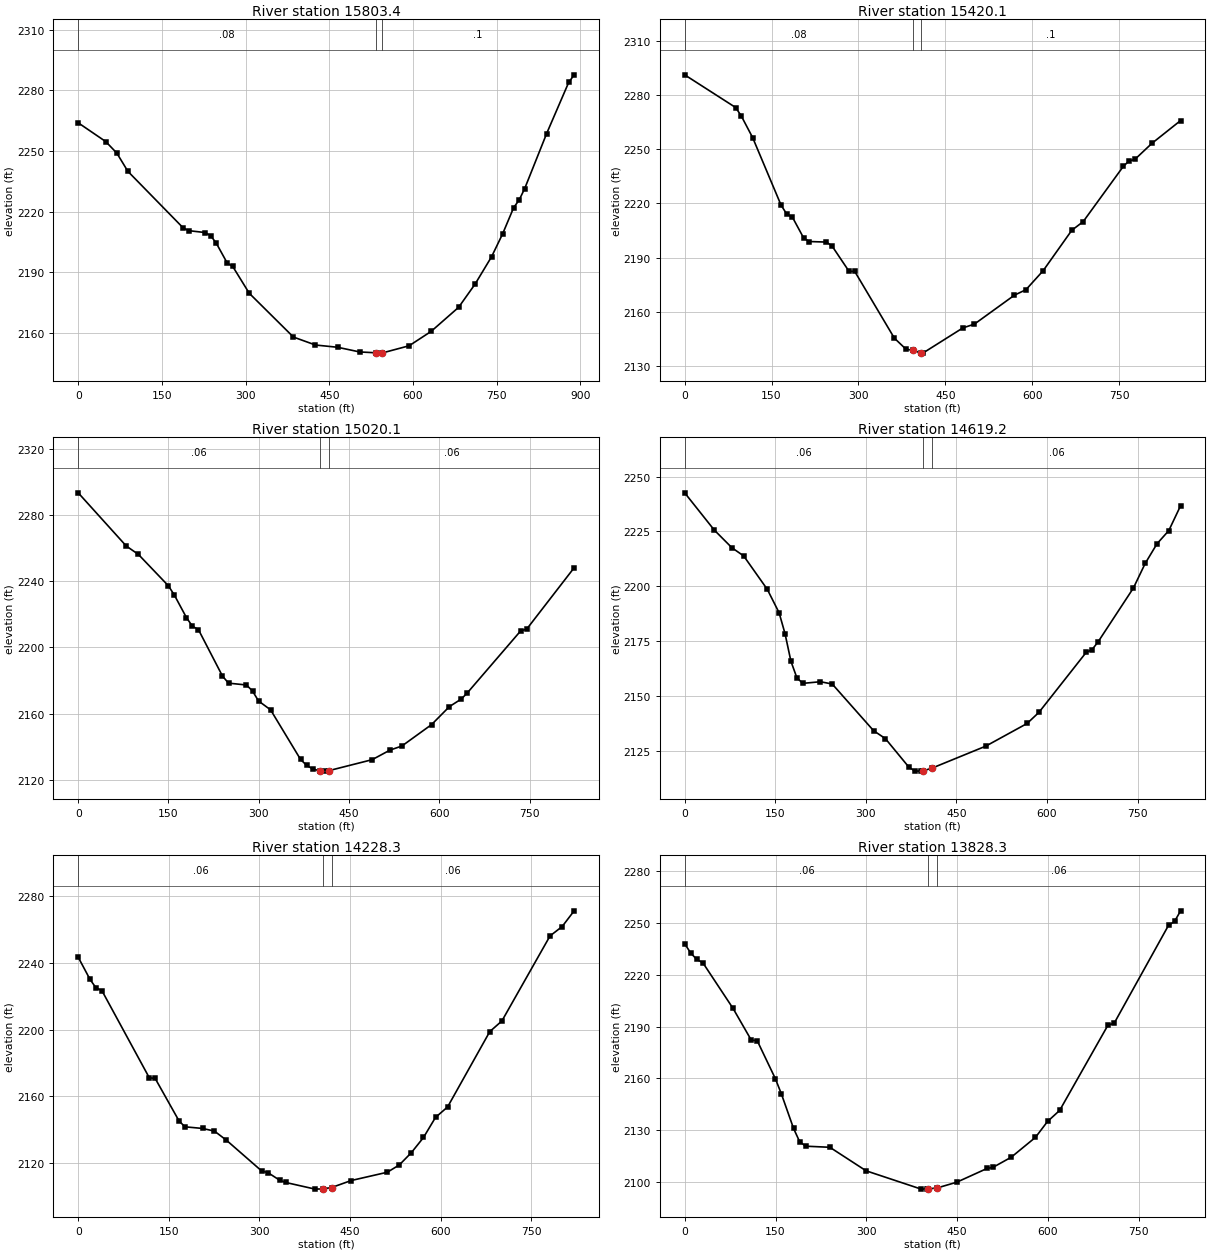
Type RM Length L Ch R = 1 ,15803.4 ,380,383.3,407.8
XS GIS Cut Line= 3
     1962261.227       125527.08     1961971.955      125125.959
      1961608.41      124972.796
#Sta/Elev= 30
       0 2263.91    49.4 2254.62    69.2 2248.94      89 2239.92   187.9 2212.02
   197.8 2210.59   227.5 2209.65   237.4 2208.09   247.3 2204.48   267.1 2194.57
     277 2192.87   306.6 2179.62   385.8 2157.96   425.3 2154.03   464.9 2152.92
   504.4 2150.61     534 2150.18   543.9 2150.02   593.2 2153.66   632.6 2160.76
   681.9 2172.68   711.5 2184.19   741.1 2197.75   760.8 2209.01   780.6 2221.99
   790.4 2225.74   800.3 2231.37   839.7 2258.62   879.2 2283.88     889 2287.64
#Mann= 3 , 0 , 0
       0     .08       0     534    .045       0   543.9      .1       0
Bank Sta=534,543.9
XS Rating Curve= 0 ,0
Exp/Cntr=0.3,0.1

Type RM Length L Ch R = 1 ,15420.1 ,402.4,400,391.3
XS GIS Cut Line= 3
      1962452.16      125467.028     1962286.547      125101.511
     1962235.645       124649.36
#Sta/Elev= 30
       0 2291.12    88.1 2273.02    97.9 2268.26   117.4 2256.37   166.4 2219.06
   176.2 2214.11     186  2212.4   205.5 2200.83   215.3 2198.92   244.7 2198.62
   254.5 2196.42   283.8 2182.43   293.6  2182.4   362.1 2145.46   381.7  2139.5
   393.8 2138.66   408.8 2137.24   411.2  2137.2   480.4 2151.16   500.2 2153.24
   569.4 2169.26   589.2 2172.27   618.9 2182.77   668.4 2205.14   688.1 2209.94
   757.4  2240.5   767.3 2243.51   777.2 2244.31   806.8 2253.24   856.3 2265.84
#Mann= 3 , 0 , 0
       0     .08       0   393.8    .045       0   408.8      .1       0
Bank Sta=393.8,408.8
XS Rating Curve= 0 ,0
Exp/Cntr=0.3,0.1

Type RM Length L Ch R = 1 ,15020.1 ,403.1,400.9,397.6
XS GIS Cut Line= 3
     1962844.467      125280.767     1962637.838       124927.29
     1962446.776       124559.34
#Sta/Elev= 30
       0 2293.31    79.9 2261.18    99.9 2256.16   149.8  2237.2   159.8 2231.55
   179.8 2218.01   189.7 2212.78   199.7 2210.76   239.7 2182.69   249.7 2178.43
   279.6  2177.3   289.6 2173.67   299.6 2167.65   319.6 2162.32   369.5 2132.33
   379.5  2128.8   389.5 2126.65   401.9 2125.41   409.4 2125.31   416.9 2125.64
   488.4 2132.22     518    2138   537.8 2140.47   587.1  2153.4   616.7 2164.25
   636.5 2168.84   646.4  2172.5   735.2    2210   745.1 2211.01     824 2248.09
#Mann= 3 , 0 , 0
       0     .06       0   401.9    .045       0   416.9     .06       0
Bank Sta=401.9,416.9
XS Rating Curve= 0 ,0
Exp/Cntr=0.3,0.1

Type RM Length L Ch R = 1 ,14619.2 ,376.5,390.7,405.6
XS GIS Cut Line= 3
     1963234.201       125087.58     1962993.072        124755.2
      1962753.19      124421.737
#Sta/Elev= 30
       0 2242.64    48.9 2225.69    78.2  2217.6    97.8 2213.83   136.9 2198.58
   156.4 2187.92   166.2  2178.4     176 2165.78   185.8 2158.29   195.5 2155.72
   224.9 2156.47   244.4 2155.42   312.9 2134.13   332.4 2130.53   371.5 2117.45
   381.3 2115.76   391.1 2115.69   395.1 2115.81   410.1 2117.11   498.7 2127.09
   567.1 2137.42   586.7 2142.49   664.9 2169.83   674.7 2171.12   684.5 2174.57
   743.2 2199.22   762.7 2210.42   782.3 2219.41   801.8 2225.41   821.4 2236.79
#Mann= 3 , 0 , 0
       0     .06       0   395.1    .045       0   410.1     .06       0
Bank Sta=395.1,410.1
XS Rating Curve= 0 ,0
Exp/Cntr=0.3,0.1

Type RM Length L Ch R = 1 ,14228.3 ,405.5,400,393.3
XS GIS Cut Line= 3
     1963352.255      125046.414     1963352.109      124634.359
     1963365.884      124225.302
#Sta/Elev= 30
       0 2243.36    19.6 2230.03    29.4 2225.02    39.2 2223.36   117.7 2171.09
   127.5 2170.65   166.8 2145.32   176.6 2141.68     206 2140.69   225.6  2139.1
   245.3 2133.68   304.1 2115.11     314 2114.25   333.6 2109.66   343.4 2108.32
   392.4 2104.31   404.6 2104.47   419.6 2105.27     452 2109.46   511.9 2114.44
   531.8 2118.83   551.8 2126.21   571.8 2135.27   591.7 2147.31   611.7 2153.58
   681.6 2198.77   701.6 2205.13   781.4 2256.15   801.4 2261.75   821.3 2271.18
#Mann= 3 , 0 , 0
       0     .06       0   404.6    .045       0   419.6     .06       0
Bank Sta=404.6,419.6
XS Rating Curve= 0 ,0
Exp/Cntr=0.3,0.1

Type RM Length L Ch R = 1 ,13828.3 ,332.9,326.3,320.1
XS GIS Cut Line= 3
     1963836.443      124945.558     1963736.863      124548.272
     1963630.406      124152.866
#Sta/Elev= 30
       0 2237.88      10 2232.49      20 2228.81      30 2226.89    79.9 2200.49
   109.9 2182.21   119.9 2181.76   149.8 2159.85   159.8 2150.99   179.8 2131.13
   189.8  2123.5   199.8 2120.84   239.8 2120.21   299.7  2106.6   389.6 2096.15
   399.6 2096.02   402.1 2096.16   417.1 2096.71   449.5 2100.04   499.5 2107.99
   509.4 2108.65   539.4 2114.48   579.4 2125.96   599.3 2135.14   619.3 2141.51
   699.2 2190.87   709.2 2191.82   799.1  2248.5   809.1 2250.79   819.1  2256.9
#Mann= 3 , 0 , 0
       0     .06       0   402.1    .045       0   417.1     .06       0
Bank Sta=402.1,417.1
XS Rating Curve= 0 ,0
Exp/Cntr=0.3,0.1

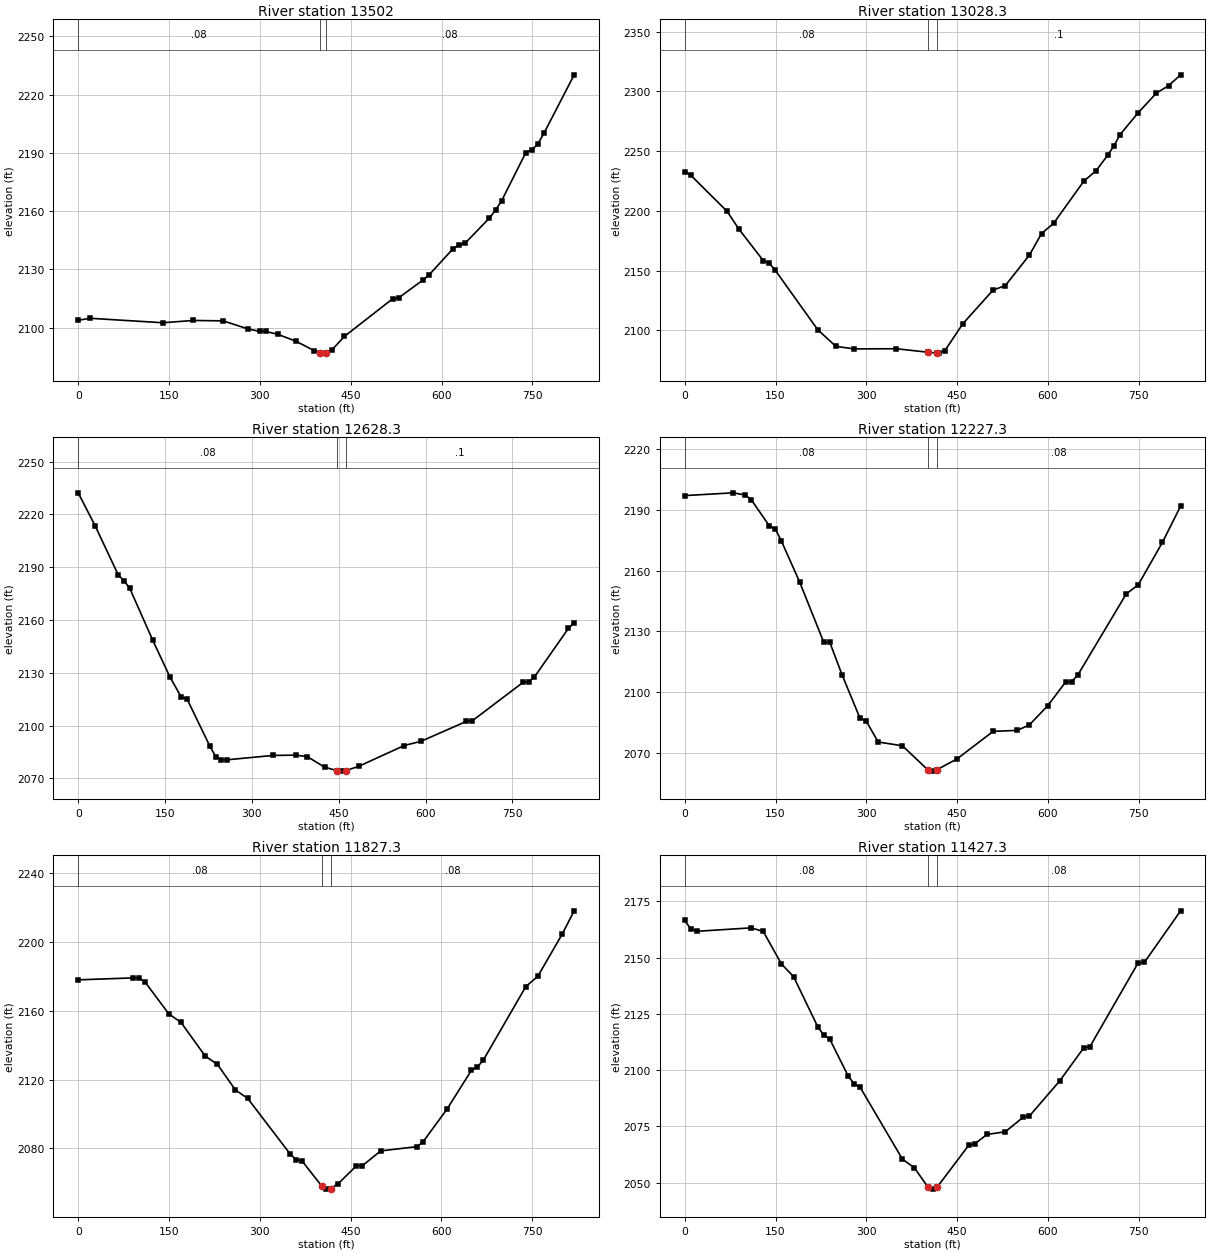
Type RM Length L Ch R = 1 ,13502   ,478.5,473.7,468.9
XS GIS Cut Line= 3
     1964256.713      124806.653     1964048.148      124454.248
     1963837.744      124102.927
#Sta/Elev= 30
       0  2103.8      20  2104.8   139.8 2102.51   189.8 2103.69   239.7 2103.47
   279.7 2099.37   299.6 2098.06   309.6 2098.05   329.6 2096.55   359.6 2092.99
   389.5 2088.15   399.5 2086.94   409.5 2086.86   419.5 2088.68   439.5 2095.44
   519.4 2114.89   529.4 2115.38   569.3 2124.51   579.3 2127.11   619.2 2140.72
   629.2 2142.58   639.2 2143.58   679.2 2156.46   689.2 2160.54   699.2 2165.32
   739.1 2190.12   749.1 2191.52   759.1 2194.64   769.1 2200.09     819 2230.21
#Mann= 3 , 0 , 0
       0     .08       0   399.5    .045       0   409.5     .08       0
Bank Sta=399.5,409.5
XS Rating Curve= 0 ,0
Exp/Cntr=0.3,0.1

Type RM Length L Ch R = 1 ,13028.3 ,388.8,400,414.1
XS GIS Cut Line= 3
     1964689.293       124453.72     1964410.486      124153.791
     1964131.679      123853.863
#Sta/Elev= 30
       0 2232.92      10 2229.84    69.9 2199.67    89.9 2184.48   129.8 2158.34
   139.8 2156.16   149.8 2150.09   219.7 2100.45   249.7 2086.51   279.7  2084.4
   349.6 2084.52     402  2081.6     417 2080.93   419.5 2080.85   429.5  2082.8
   459.4 2105.48   509.4 2133.72   529.4 2137.35   569.3 2162.96   589.3 2180.94
   609.3 2189.59   659.2 2224.87   679.2 2233.52   699.2    2247   709.1 2254.65
   719.1  2263.9   749.1 2282.23     779 2298.62     799 2304.76     819  2313.9
#Mann= 3 , 0 , 0
       0     .08       0     402    .045       0     417      .1       0
Bank Sta=402,417
XS Rating Curve= 0 ,0
Exp/Cntr=0.3,0.1

Type RM Length L Ch R = 1 ,12628.3 ,400.3,400.9,398.6
XS GIS Cut Line= 3
      1964830.91       124339.99     1964709.541       123901.22
     1964652.772      123503.828
#Sta/Elev= 30
       0 2232.21    29.7 2213.15    69.3 2185.49    79.2 2182.28    89.1  2177.9
   128.7 2148.52   158.4 2127.66   178.1 2116.12     188 2115.11   227.6 2088.18
   237.5 2082.41   247.4 2080.53   257.3 2080.58   336.5 2083.05   376.1 2083.23
   395.9 2082.34   425.6  2076.4   447.7 2074.34   455.2 2074.14   462.7 2074.48
   484.6 2076.88     563 2088.65   592.3 2091.11   670.6 2102.39   680.4 2102.64
   768.6 2124.59   778.4 2124.84   788.1 2127.64   846.9 2155.25   856.7 2158.42
#Mann= 3 , 0 , 0
       0     .08       0   447.7    .045       0   462.7      .1       0
Bank Sta=447.7,462.7
XS Rating Curve= 0 ,0
Exp/Cntr=0.3,0.1

Type RM Length L Ch R = 1 ,12227.3 ,398.3,400,401.3
XS GIS Cut Line= 3
     1965199.797      124302.335     1965102.586      123904.541
     1965005.376      123506.746
#Sta/Elev= 30
       0 2197.14    79.9 2198.51    99.9 2197.44   109.9 2195.13   139.8 2182.18
   149.8 2180.58   159.8 2174.63   189.8 2154.44   229.7  2124.6   239.7 2124.54
   259.7 2108.68   289.6 2087.01   299.6 2085.74   319.6  2075.3   359.6 2073.45
     402  2061.4   409.5 2060.91     417 2061.69   449.4 2066.88   509.4 2080.56
   549.3 2081.06   569.3 2083.77   599.3 2093.18   629.2    2105   639.2 2105.22
   649.2 2108.43   729.1 2148.47   749.1 2153.09     789 2174.05     819 2191.94
#Mann= 3 , 0 , 0
       0     .08       0     402    .045       0     417     .08       0
Bank Sta=402,417
XS Rating Curve= 0 ,0
Exp/Cntr=0.3,0.1

Type RM Length L Ch R = 1 ,11827.3 ,394.4,400,406
XS GIS Cut Line= 3
     1965561.875      124232.419     1965494.744      123828.376
     1965420.321       123425.71
#Sta/Elev= 30
       0    2178    89.9 2179.12    99.9 2178.99   109.9 2176.95   149.8 2158.14
   169.8 2153.25   209.8 2133.65   229.8 2128.92   259.7 2113.93   279.7 2109.14
   349.6 2076.94   359.6 2073.46   369.6 2072.73   402.1 2058.14   409.6  2056.3
   417.1  2056.6   429.6 2059.54   459.5 2069.89   469.5 2069.96   499.5 2078.52
   559.4    2081   569.4 2083.73   609.3 2102.92   649.3 2125.32   659.3 2127.31
   669.3 2131.46   739.2 2174.04   759.1 2180.08   799.1 2204.41   819.1 2218.13
#Mann= 3 , 0 , 0
       0     .08       0   402.1    .045       0   417.1     .08       0
Bank Sta=402.1,417.1
XS Rating Curve= 0 ,0
Exp/Cntr=0.3,0.1

Type RM Length L Ch R = 1 ,11427.3 ,399.2,400.3,401.4
XS GIS Cut Line= 3
     1965858.479      124245.233     1965893.205      123837.208
      1965927.93      123429.183
#Sta/Elev= 30
       0  2166.6      10 2162.78      20 2161.73   109.9 2163.26   129.8 2161.65
   159.8 2147.19   179.8 2141.59   219.7 2119.31   229.7 2115.57   239.7 2113.74
   269.7 2097.55   279.7 2093.93   289.6 2092.45   359.6 2060.42   379.5 2056.54
     402 2047.89   409.5  2047.1     417 2048.02   469.4 2066.71   479.4 2067.35
   499.4 2071.42   529.4 2072.58   559.3 2079.14   569.3 2079.58   619.2 2095.17
   659.2 2109.99   669.2 2110.42   749.1 2147.82   759.1 2147.89     819 2170.83
#Mann= 3 , 0 , 0
       0     .08       0     402    .045       0     417     .08       0
Bank Sta=402,417
XS Rating Curve= 0 ,0
Exp/Cntr=0.3,0.1

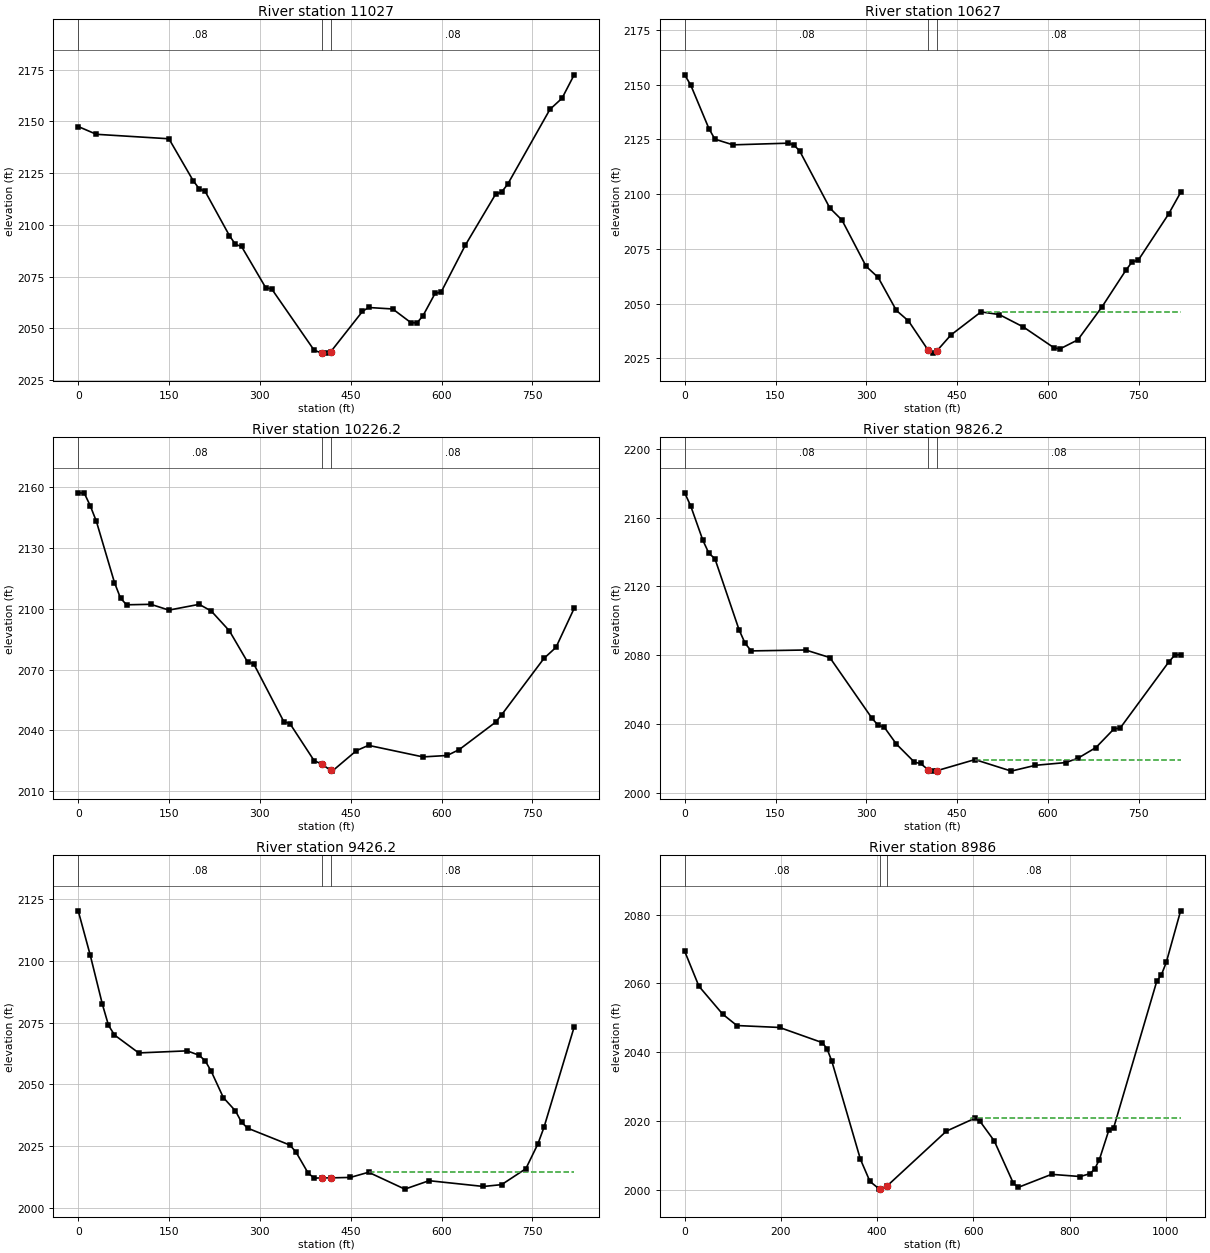
Type RM Length L Ch R = 1 ,11027   ,400.8,400,399.2
XS GIS Cut Line= 3
      1966237.43      124275.074      1966291.72      123869.189
      1966346.01      123463.304
#Sta/Elev= 30
       0 2147.48      30 2143.73   149.8 2141.57   189.8 2121.37   199.8 2117.44
   209.7 2116.12   249.7 2094.82   259.7 2090.56   269.7 2089.59   309.6  2069.7
   319.6 2069.04   389.5 2039.53     402  2038.1   409.5 2038.09     417 2038.74
   469.4 2058.22   479.4 2060.12   519.4  2059.4   549.3 2052.83   559.3 2052.65
   569.3 2056.11   589.3 2066.91   599.3 2067.56   639.2 2090.16   689.2 2114.77
   699.2 2115.87   709.1 2119.57     779 2155.76     799 2161.14     819 2172.44
#Mann= 3 , 0 , 0
       0     .08       0     402    .045       0     417     .08       0
Bank Sta=402,417
XS Rating Curve= 0 ,0
Exp/Cntr=0.3,0.1

Type RM Length L Ch R = 1 ,10627   ,400.9,400.8,400.7
XS GIS Cut Line= 3
     1966648.483      124323.026      1966688.98      123915.534
     1966729.476      123508.041
#Sta/Elev= 30
       0 2154.45      10 2149.77      40 2129.93    49.9 2125.07    79.9 2122.48
   169.8 2123.24   179.8 2122.57   189.8 2119.73   239.7 2093.64   259.7 2088.15
   299.6 2067.03   319.6 2061.92   349.6 2046.87   369.6 2042.08     402 2028.76
   409.5 2027.39     417 2028.58   439.5 2035.63   489.4 2046.22   519.4 2045.01
   559.3 2039.33   609.3 2029.94   619.2 2029.25   649.2 2033.44   689.2 2048.52
   729.1 2065.45   739.1 2069.09   749.1 2069.83     799 2090.83     819 2100.75
#Mann= 3 , 0 , 0
       0     .08       0     402    .045       0     417     .08       0
#XS Ineff= 2 , 0
                          499.15         2046.08
Permanent Ineff=
       F       F
Bank Sta=402,417
XS Rating Curve= 0 ,0
Exp/Cntr=0.3,0.1

Type RM Length L Ch R = 1 ,10226.2 ,400.8,400,399.2
XS GIS Cut Line= 3
     1967048.964      124359.227     1967087.348      123951.499
      1967126.04      123543.862
#Sta/Elev= 30
       0 2157.23      10  2157.1      20 2150.76      30 2143.15    59.9 2112.92
    69.9 2105.22    79.9 2101.97   119.9 2102.21   149.8 2099.35   199.8  2102.2
   219.8 2098.87   249.7  2089.1   279.7 2073.72   289.7 2072.92   339.6 2044.26
   349.6 2043.36   389.6 2025.04   402.1 2023.39   417.1 2020.19   419.5 2019.88
   459.5    2030   479.4  2032.6   569.3  2026.9   609.3  2027.6   629.2 2030.51
   689.2 2044.02   699.2 2047.67   769.1 2075.51     789 2080.97     819 2100.21
#Mann= 3 , 0 , 0
       0     .08       0   402.1    .045       0   417.1     .08       0
Bank Sta=402.1,417.1
XS Rating Curve= 0 ,0
Exp/Cntr=0.3,0.1

Type RM Length L Ch R = 1 ,9826.2  ,401,400,398.7
XS GIS Cut Line= 3
     1967462.018      124396.581     1967485.632      123987.763
     1967509.246      123578.944
#Sta/Elev= 30
       0 2174.38      10  2166.7      30 2146.81      40  2139.2    49.9 2136.12
    89.9 2094.64    99.9 2086.79   109.9 2082.44   199.8 2082.97   239.7 2078.57
   309.6 2043.13   319.6 2039.15   329.6 2038.06   349.6 2028.26   379.5 2017.69
   389.5 2016.97     402 2013.36   409.5 2012.52     417 2012.82   479.4 2019.23
   539.3 2012.54   579.3 2015.91   629.2 2017.49   649.2 2019.98   679.2 2026.25
   709.1 2037.14   719.1 2037.51     799  2075.8     809 2079.88     819 2080.32
#Mann= 3 , 0 , 0
       0     .08       0     402    .045       0     417     .08       0
#XS Ineff= 2 , 0
                          479.37         2019.25
Permanent Ineff=
       F       F
Bank Sta=402,417
XS Rating Curve= 0 ,0
Exp/Cntr=0.3,0.1

Type RM Length L Ch R = 1 ,9426.2  ,435.6,440.1,445
XS GIS Cut Line= 3
     1967878.849      124415.734     1967885.099      124006.224
     1967885.099      123596.734
#Sta/Elev= 30
       0 2120.39      20 2102.28      40 2082.42      50 2073.98    59.9 2070.04
    99.9 2062.77   179.8 2063.61   199.8 2061.82   209.8 2059.54   219.8 2055.25
   239.7 2044.64   259.7 2039.26   269.7 2034.68   279.7 2032.27   349.6  2025.4
   359.6 2022.58   379.6 2014.08   389.6    2012   402.1  2012.1   417.1  2012.1
   449.5 2012.29   479.5 2014.38   539.4 2007.54   579.4 2010.96   669.2 2008.62
   699.2 2009.36   739.2 2015.81   759.1 2025.86   769.1 2032.54     819 2073.28
#Mann= 3 , 0 , 0
       0     .08       0   402.1    .045       0   417.1     .08       0
#XS Ineff= 2 , 0
                          479.93         2014.47
Permanent Ineff=
       F       F
Bank Sta=402.1,417.1
XS Rating Curve= 0 ,0
Exp/Cntr=0.3,0.1

Type RM Length L Ch R = 1 ,8986    ,577,578.2,579.4
XS GIS Cut Line= 3
     1968064.262      124485.467     1968269.788      124233.021
     1968420.165      123543.794
#Sta/Elev= 30
       0 2069.35    29.6 2059.19    78.9 2051.08   108.5 2047.76   197.3  2047.2
   286.1 2042.79   295.9 2041.01   305.8 2037.44   365.3 2008.89   385.2 2002.42
     405  2000.2   405.3  2000.2   420.3 2001.06   544.1 2017.06   603.7 2020.85
   613.7 2019.96   643.5 2014.24   683.2 2001.94   693.2  2000.7   762.7  2004.5
   822.3 2003.86   842.2 2004.68   852.1 2005.99   862.1 2008.78   881.9  2017.4
   891.9 2018.08   981.3 2060.58   991.2 2062.56  1001.2 2066.14    1031 2081.11
#Mann= 3 , 0 , 0
       0     .08       0   405.3    .045       0   420.3     .08       0
#XS Ineff= 2 , 0
                          594.91         2020.79
Permanent Ineff=
       F       F
Bank Sta=405.3,420.3
XS Rating Curve= 0 ,0
Exp/Cntr=0.3,0.1

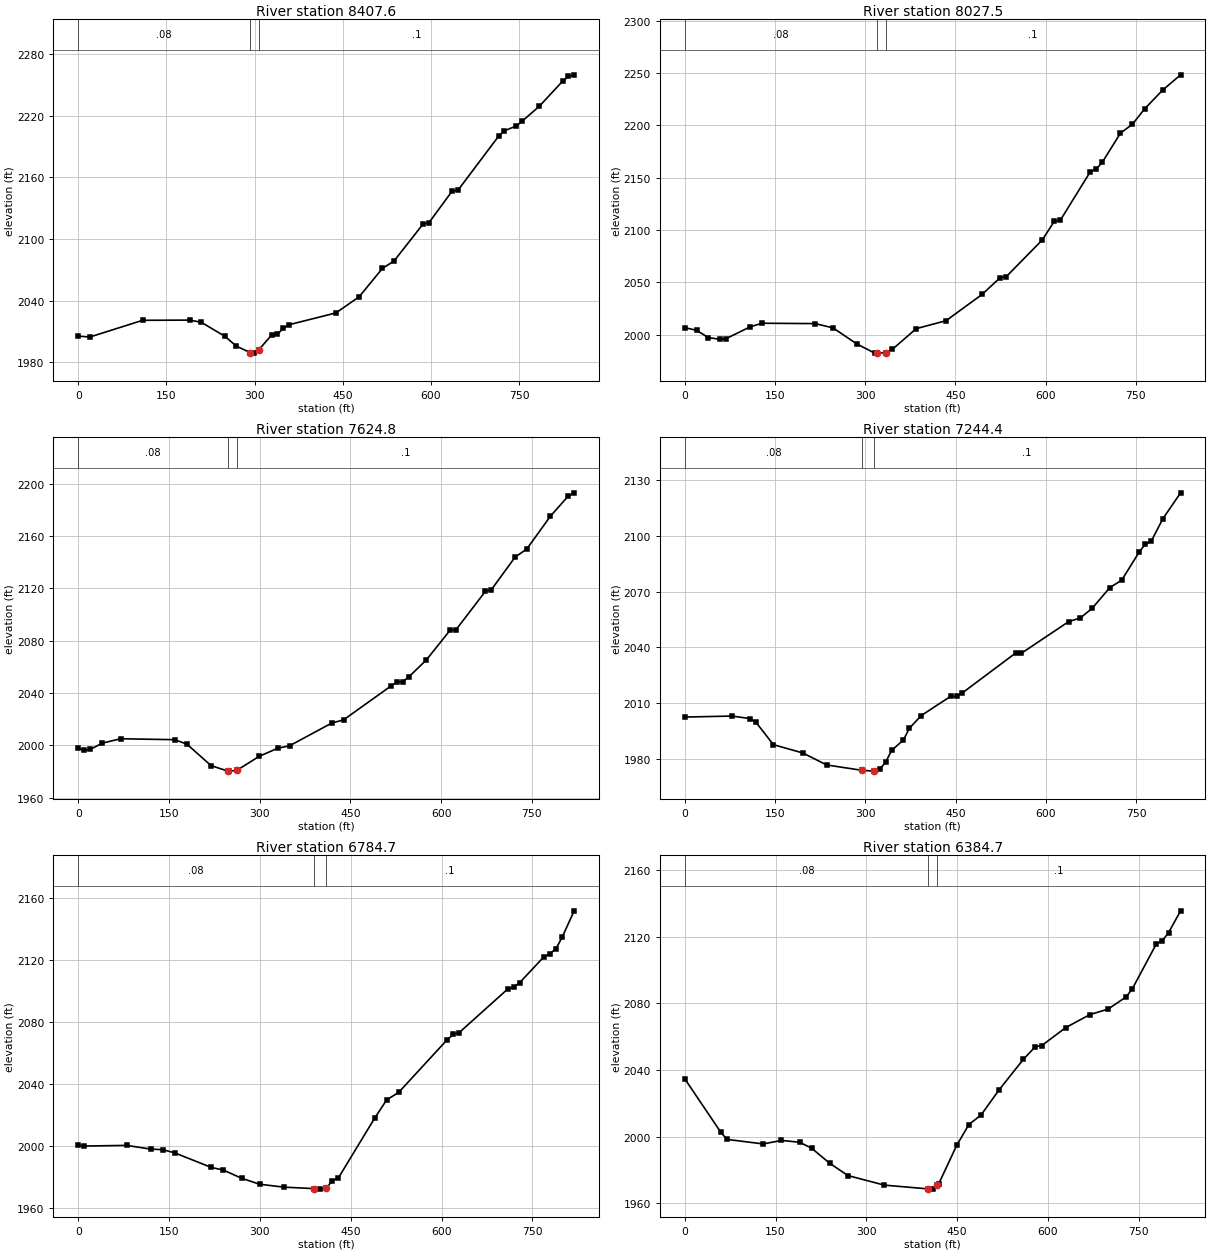
Type RM Length L Ch R = 1 ,8407.6  ,384.1,380.2,376.2
XS GIS Cut Line= 3
     1968765.034      124585.144      1968879.12      124172.141
      1968973.03      123767.793
#Sta/Elev= 30
       0  2005.4    19.9 2004.57   109.6 2020.82   189.3 2021.02   209.2 2018.96
   249.1 2005.35     269 1995.68   292.5 1989.39   298.9 1988.84   307.5 1992.34
   328.8 2006.31   338.8 2007.13   348.8 2013.15   358.7 2016.54   438.4 2028.02
   477.9 2043.77   517.4 2071.34   537.2 2078.62   586.6 2114.64   596.5 2115.84
     636  2146.7   645.9 2147.51   715.1 2200.25     725 2205.48   744.8 2210.12
   754.6 2214.58   784.3 2229.35   823.8 2253.73   833.7 2258.41   843.6 2260.02
#Mann= 3 , 0 , 0
       0     .08       0   292.5    .045       0   307.5      .1       0
Bank Sta=292.5,307.5
XS Rating Curve= 0 ,0
Exp/Cntr=0.3,0.1

Type RM Length L Ch R = 1 ,8027.5  ,403.7,402.9,402
XS GIS Cut Line= 3
     1969187.679      124687.556     1969227.446      124274.996
     1969322.725       123876.35
#Sta/Elev= 30
       0 2006.65    19.7 2004.05    39.5 1997.03    59.2 1995.45    69.1 1996.17
   108.6 2007.29   128.3 2010.82   217.1 2010.48   246.7 2006.35   286.2    1991
   315.8 1982.24   319.2 1982.29   334.2 1982.84   345.4 1985.97   384.9 2005.65
   434.5 2013.27   494.4  2038.4   524.4 2054.39   534.4 2055.28   594.4 2090.45
   614.4 2108.27   624.4 2109.26   674.4 2155.81   684.4 2158.39   694.4  2164.9
   724.4 2192.64   744.4 2201.17   764.4 2215.73   794.4 2233.71   824.4 2248.39
#Mann= 3 , 0 , 0
       0     .08       0   319.2    .045       0   334.2      .1       0
Bank Sta=319.2,334.2
XS Rating Curve= 0 ,0
Exp/Cntr=0.3,0.1

Type RM Length L Ch R = 1 ,7624.8  ,356.1,380.1,397.1
XS GIS Cut Line= 3
     1969599.315      124693.898     1969623.352      124285.276
     1969621.817      123874.807
#Sta/Elev= 30
       0 1997.69      10  1996.1      20 1996.84    39.9 2001.57    69.9 2004.93
   159.7 2004.22   179.7  2000.8   219.6 1984.39   247.1 1980.26   249.6 1980.18
   262.1 1980.76   299.5 1991.58   329.5 1997.61   349.4 1999.57   419.1 2016.94
   438.6 2019.37   516.8 2045.21   526.6  2048.1   536.4 2048.56   546.2 2052.09
   575.5  2065.2   614.6 2087.87   624.3 2088.17   673.2 2117.72     683 2118.92
   722.1 2143.77   741.6 2150.08   780.7 2175.18     810 2190.49   819.8 2192.98
#Mann= 3 , 0 , 0
       0     .08       0   247.1    .045       0   262.1      .1       0
Bank Sta=247.1,262.1
XS Rating Curve= 0 ,0
Exp/Cntr=0.3,0.1

Type RM Length L Ch R = 1 ,7244.4  ,479.6,459.5,446.5
XS GIS Cut Line= 3
      1969885.55       124691.18     1970007.961      124297.357
     1970150.668       123911.65
#Sta/Elev= 30
       0 2002.52    78.6 2003.07     108 2001.71   117.8 1999.99   147.3 1987.66
   196.4 1983.16   235.7 1976.73   294.6 1973.83   314.2  1973.4     324 1974.48
   333.8 1978.21   343.7 1984.57   363.3 1990.15   373.1 1996.43   392.8 2003.32
   441.8  2013.7   451.6 2013.69   461.4 2015.59   549.5 2036.97   559.3 2036.91
   637.6  2053.9   657.2 2055.94   676.8  2061.1   706.2 2072.29   725.8 2076.25
   755.1 2091.53   764.9 2095.64   774.7 2097.12   794.3 2109.42   823.7 2123.32
#Mann= 3 , 0 , 0
       0     .08       0   294.6    .045       0   314.2      .1       0
Bank Sta=294.6,314.2
XS Rating Curve= 0 ,0
Exp/Cntr=0.3,0.1

Type RM Length L Ch R = 1 ,6784.7  ,398,400,402
XS GIS Cut Line= 3
      1970294.21      124766.979     1970399.461      124371.236
     1970504.712      123975.493
#Sta/Elev= 30
       0 2000.68      10 2000.08    79.9 2000.51   119.8 1998.11   139.8 1997.74
   159.8 1995.63   219.7 1986.32   239.7 1984.61   269.7 1979.35   299.6 1975.48
   339.6 1973.61   389.5 1972.66   399.5 1972.33   409.5 1972.76   419.5  1977.8
   429.5 1979.45   489.4 2017.96   509.4 2029.82   529.4 2034.72   609.3 2068.57
   619.2 2071.96   629.2 2073.19   709.1 2101.17   719.1 2102.39   729.1 2105.35
   769.1 2122.02     779    2124     789 2127.25     799 2134.46     819 2151.62
#Mann= 3 , 0 , 0
       0     .08       0   389.5    .045       0   409.5      .1       0
Bank Sta=389.5,409.5
XS Rating Curve= 0 ,0
Exp/Cntr=0.3,0.1

Type RM Length L Ch R = 1 ,6384.7  ,406.4,400,393.3
XS GIS Cut Line= 3
     1970627.686      124904.009     1970767.918      124519.269
      1970907.39      124134.251
#Sta/Elev= 30
       0  2034.8    59.9  2002.5    69.9 1998.35   129.8 1995.61   159.8 1997.72
   189.8 1996.63   209.7 1993.03   239.7 1983.94   269.7 1976.61   329.6 1970.89
     402 1968.62   409.5 1968.48     417 1970.85   419.5 1971.64   449.4  1994.9
   469.4 2007.28   489.4 2012.97   519.4 2028.19   559.3 2046.42   579.3 2054.11
   589.3 2054.56   629.2 2065.46   669.2 2073.29   699.2 2076.57   729.1 2083.92
   739.1 2088.68     779 2115.79     789 2117.74     799 2122.46     819 2135.59
#Mann= 3 , 0 , 0
       0     .08       0     402    .045       0     417      .1       0
Bank Sta=402,417
XS Rating Curve= 0 ,0
Exp/Cntr=0.3,0.1

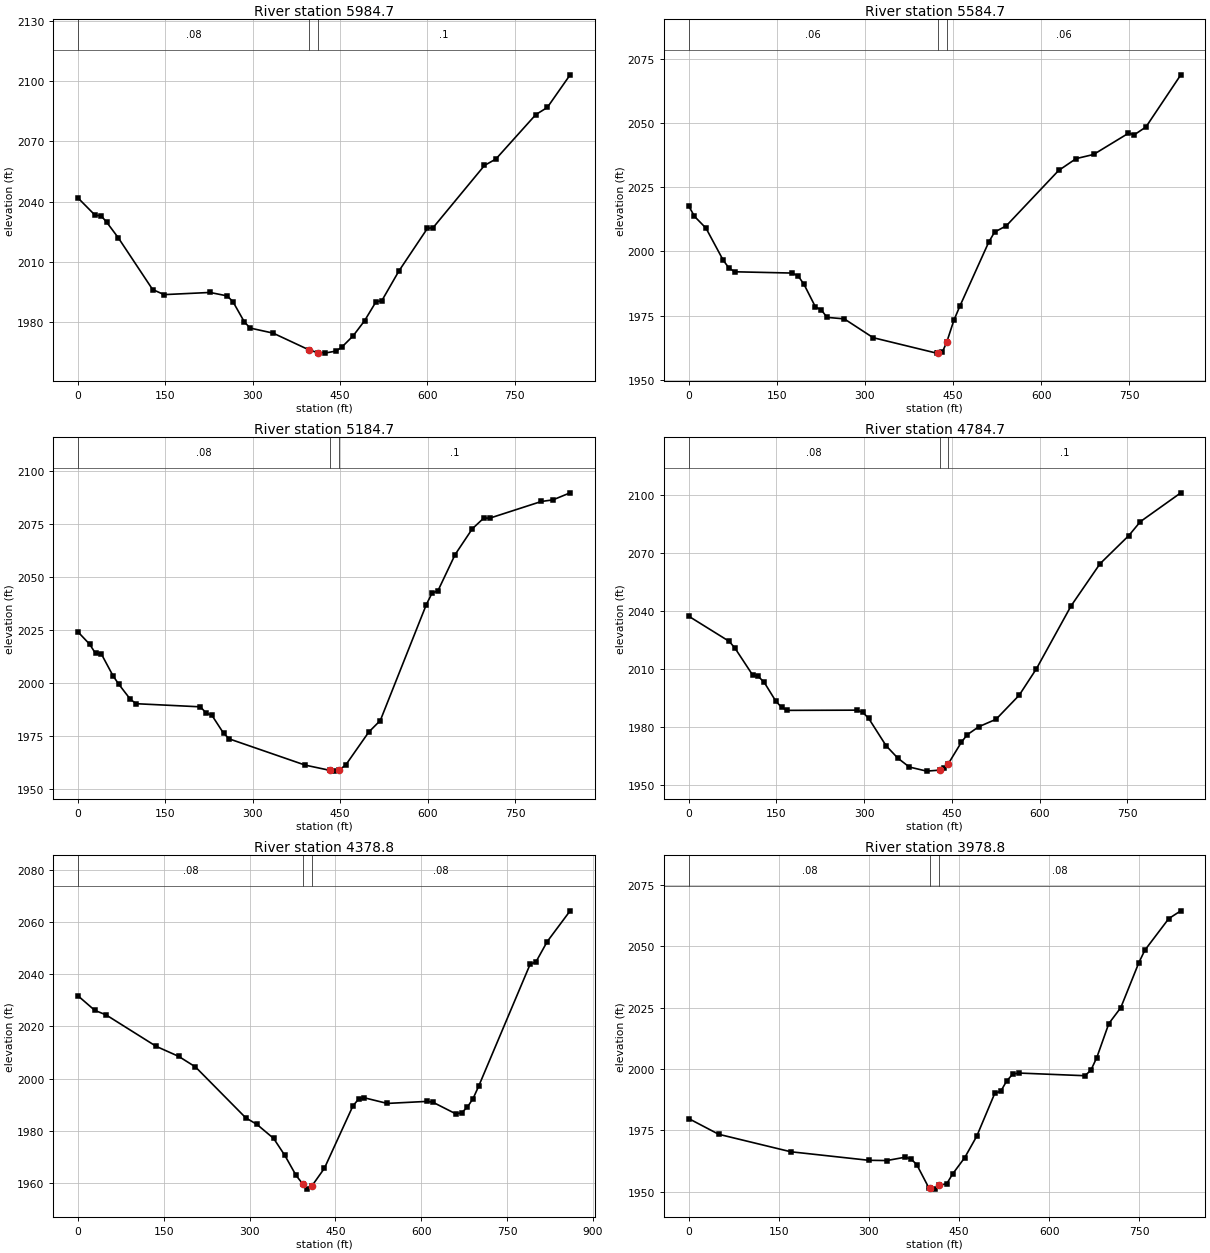
Type RM Length L Ch R = 1 ,5984.7  ,395.3,400,411.6
XS GIS Cut Line= 3
     1971113.014      125059.243     1971139.883      124656.224
     1971162.384       124215.64
#Sta/Elev= 30
       0 2041.83    29.6 2033.14    39.4 2033.05    49.3 2029.73      69 2022.06
   128.1 1996.23   147.8 1993.69   226.6 1994.77   256.1 1993.06     266 1990.19
   285.7 1980.07   295.6 1977.03     335 1974.52   396.4  1966.2   411.4 1964.78
   423.5 1964.55   443.1 1965.58   452.9 1967.51   472.5 1973.17   492.1 1980.68
   511.8 1990.17   521.6 1990.61     551 2005.44     600 2026.69   609.8 2027.06
     698 2058.03   717.6 2061.23   786.2 2083.37   805.9 2086.91   845.1 2103.17
#Mann= 3 , 0 , 0
       0     .08       0   396.4    .045       0   411.4      .1       0
Bank Sta=396.4,411.4
XS Rating Curve= 0 ,0
Exp/Cntr=0.3,0.1

Type RM Length L Ch R = 1 ,5584.7  ,402.5,400,385.3
XS GIS Cut Line= 3
     1971398.449      125044.392     1971515.695      124629.056
     1971729.775      124284.022
#Sta/Elev= 30
       0 2017.67     9.8 2013.61    29.4 2009.02    58.8 1996.51    68.7 1993.46
    78.5 1992.04   176.6 1991.54   186.4 1990.36   196.2 1987.18   215.8 1978.32
   225.6 1977.25   235.4  1974.3   264.8 1973.72   313.9  1966.4   421.8 1960.39
   424.1 1960.48   431.6 1960.76   439.1 1964.59   451.4  1973.2   461.3 1978.54
   510.8 2003.64   520.7  2007.5   540.5 2009.91   629.6 2031.45   659.4 2036.07
   689.1 2037.68   748.5 2045.94   758.4 2045.35   778.2 2048.36   837.6 2068.67
#Mann= 3 , 0 , 0
       0     .06       0   424.1    .045       0   439.1     .06       0
Bank Sta=424.1,439.1
XS Rating Curve= 0 ,0
Exp/Cntr=0.3,0.1

Type RM Length L Ch R = 1 ,5184.7  ,386.3,400,421
XS GIS Cut Line= 3
     1971809.652      125149.745     1971876.304      124714.952
     1971841.762      124311.672
#Sta/Elev= 30
       0 2024.12      20 2018.33      30 2014.01      40 2013.76      60 2003.49
      70 1999.44      90  1992.3     100 1990.28   209.9 1988.81   219.9 1985.92
   229.9 1984.76   249.9 1976.29   259.9 1973.65   389.9 1961.31   432.4 1958.84
   439.9 1958.48   447.4  1958.8   459.6 1961.43   499.1 1976.94   518.8 1982.36
   597.8 2037.04   607.7 2042.51   617.6 2043.48   647.2 2060.63   676.8 2072.82
   696.6  2077.9   706.4 2077.78   795.3 2085.68     815 2086.42   844.6 2089.75
#Mann= 3 , 0 , 0
       0     .08       0   432.4    .045       0   447.4      .1       0
Bank Sta=432.4,447.4
XS Rating Curve= 0 ,0
Exp/Cntr=0.3,0.1

Type RM Length L Ch R = 1 ,4784.7  ,405.1,405.9,402.9
XS GIS Cut Line= 3
     1971907.085      125198.574     1972209.462      124883.567
     1972511.653       124614.29
#Sta/Elev= 30
       0 2037.29    69.5 2024.25    79.4 2020.67   109.2 2006.97   119.1 2006.16
     129 2003.18   148.9 1993.46   158.8 1990.21   168.7 1988.67   287.8 1988.78
   297.7 1987.61   307.6 1984.59   337.4 1970.46   357.3 1964.08   377.1 1959.43
   406.9  1957.3   429.1 1957.82   436.6 1958.81   444.1 1961.23   466.3 1972.25
   476.1 1976.06   495.9 1980.21   525.5 1984.07     565 1996.46   594.6 2010.18
   653.8 2042.62   703.2 2064.34   752.6 2078.94   772.3 2086.12   841.4 2100.98
#Mann= 3 , 0 , 0
       0     .08       0   429.1    .045       0   444.1      .1       0
Bank Sta=429.1,444.1
XS Rating Curve= 0 ,0
Exp/Cntr=0.3,0.1

Type RM Length L Ch R = 1 ,4378.8  ,414,400,388
XS GIS Cut Line= 3
     1972118.813      125521.519     1972396.289       125232.48
     1972684.126      124874.253
#Sta/Elev= 30
       0 2031.78    29.3  2026.2    48.9 2024.48   136.8 2012.35   175.9 2008.52
   205.2 2004.47   293.2 1984.89   312.7 1982.37     342 1976.96   361.6 1970.42
   381.1 1962.78   393.2 1959.36   400.7 1957.49   408.2 1958.53   430.6 1965.48
   480.6 1989.51   490.6 1992.13   500.6 1992.59   540.5 1990.43   610.5 1991.22
   620.4 1990.88   660.4 1986.42   670.4 1986.83   680.4 1988.96   690.4 1992.24
   700.4 1997.09   790.3 2043.94   800.3 2044.77   820.2 2052.66   860.2 2064.46
#Mann= 3 , 0 , 0
       0     .08       0   393.2    .045       0   408.2     .08       0
Bank Sta=393.2,408.2
XS Rating Curve= 0 ,0
Exp/Cntr=0.3,0.1

Type RM Length L Ch R = 1 ,3978.8  ,407.7,406.2,404.8
XS GIS Cut Line= 3
     1972713.713        125723.9     1972778.014       125319.48
     1972842.314       124915.06
#Sta/Elev= 30
       0 1979.76    49.9 1973.36   169.8 1966.23   299.6 1962.75   329.6 1962.64
   359.6 1963.98   369.6  1963.4   379.5 1960.99   399.5 1951.59     402 1951.44
   409.5 1950.99     417  1952.6   429.5  1953.2   439.5 1957.26   459.4 1963.84
   479.4 1972.58   509.4 1990.07   519.4 1990.92   529.4 1995.16   539.3 1997.89
   549.3 1998.33   659.2 1997.24   669.2  1999.4   679.2 2004.66   699.2 2018.51
   719.1 2024.99   749.1  2043.3   759.1 2048.41     799 2061.32     819 2064.48
#Mann= 3 , 0 , 0
       0     .08       0     402    .045       0     417     .08       0
Bank Sta=402,417
XS Rating Curve= 0 ,0
Exp/Cntr=0.3,0.1