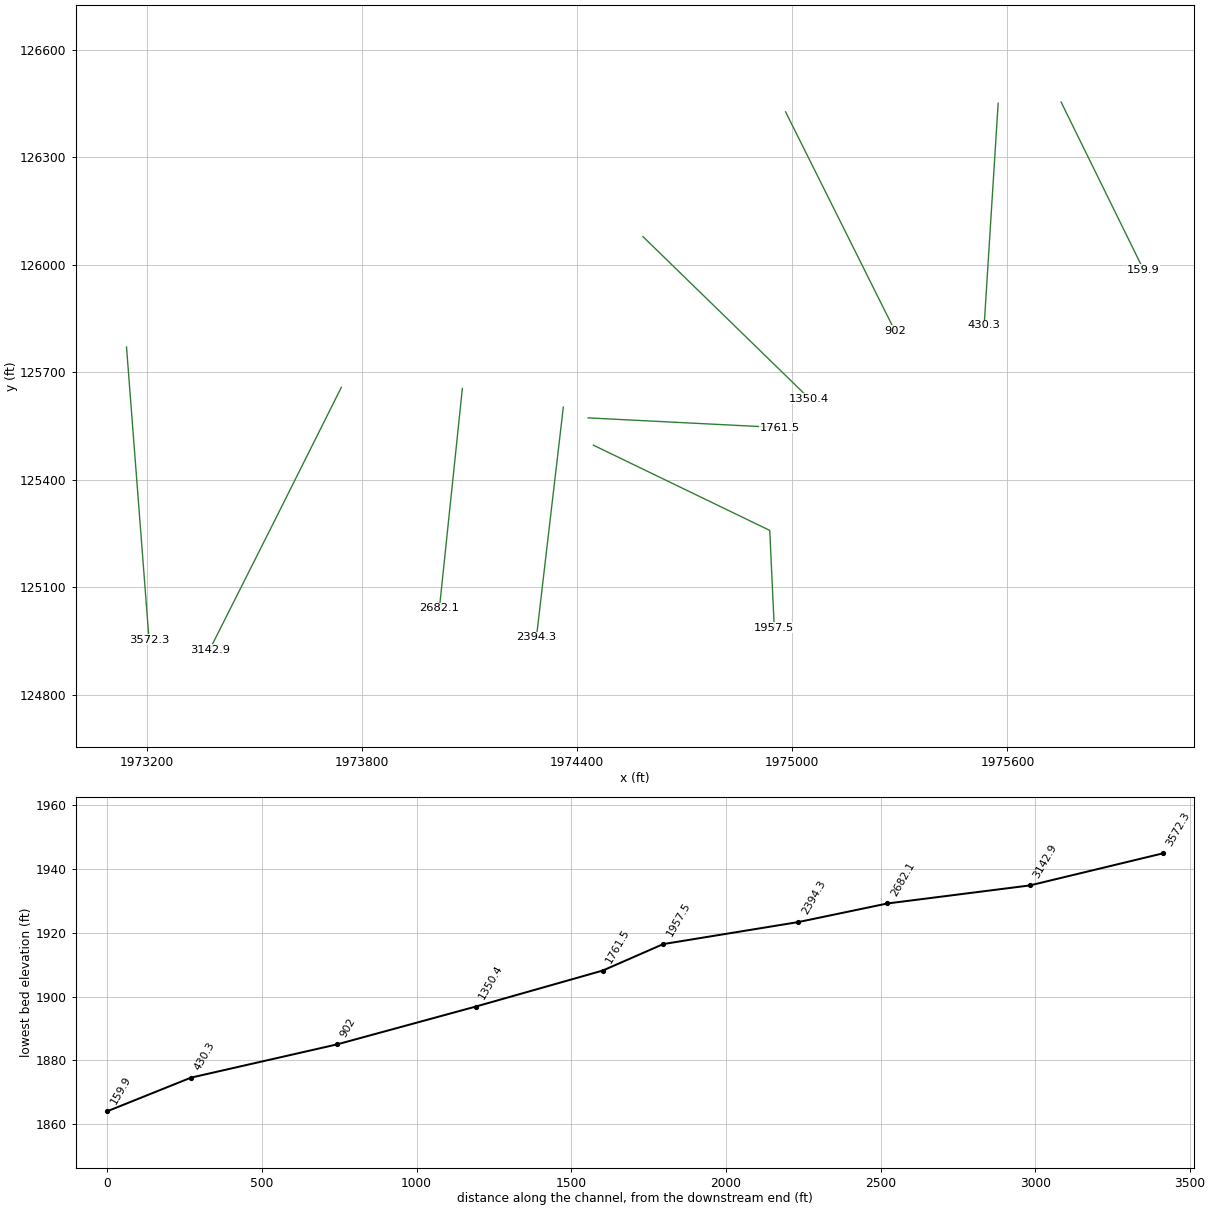
HEC-RAS study FvmlCrk.prj: FvmlCrk

--- FvmlCrk.g01 (geometry) --- (continued)

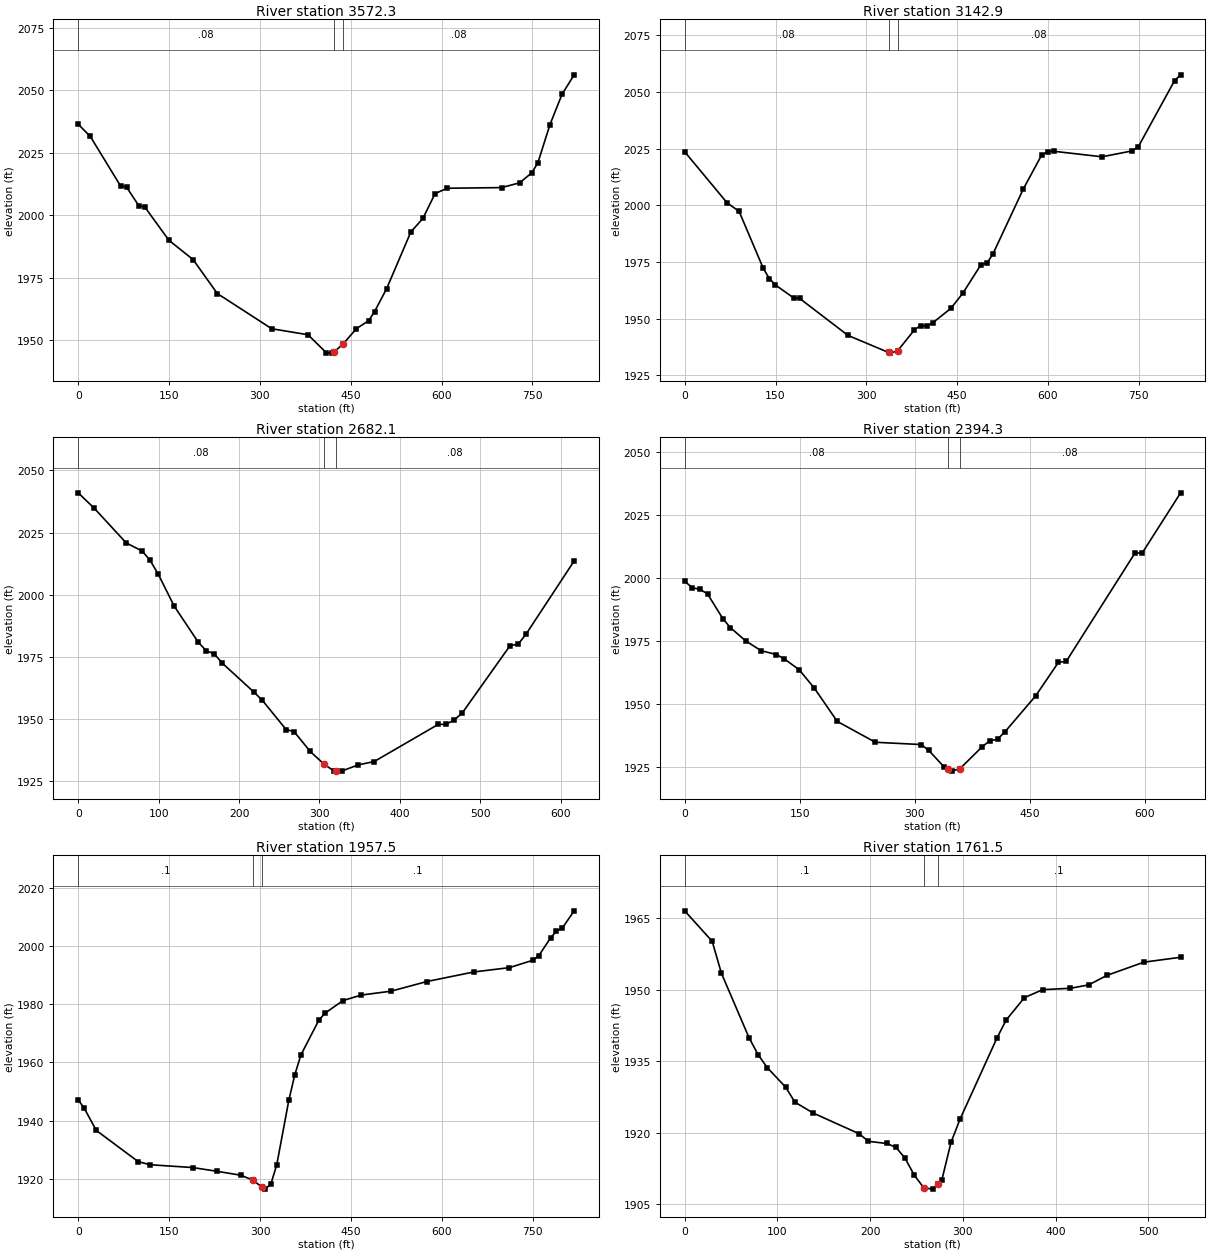
Type RM Length L Ch R = 1 ,3572.3  ,442.1,429.5,416.9
XS GIS Cut Line= 3
     1973144.229      125770.484     1973175.652      125362.192
     1973207.075      124953.899
#Sta/Elev= 30
       0 2036.38      20 2031.49    69.9  2011.7    79.9 2011.21    99.9 2003.84
   109.9  2003.3   149.8 1989.97   189.8 1982.22   229.7 1968.68   319.6 1954.59
   379.5 1952.19   409.5 1945.03   419.5 1944.84   422.4 1945.32   437.4 1948.46
   459.4 1954.64   479.4 1957.76   489.4 1961.44   509.4 1970.67   549.3  1993.3
   569.3 1998.74   589.3 2008.64   609.3 2010.78   699.2 2011.04   729.1 2012.96
   749.1 2016.98   759.1 2020.97     779  2036.2     799 2048.37     819 2056.14
#Mann= 3 , 0 , 0
       0     .08       0   422.4    .045       0   437.4     .08       0
Bank Sta=422.4,437.4
XS Rating Curve= 0 ,0
Exp/Cntr=0.3,0.1

Type RM Length L Ch R = 1 ,3142.9  ,452.4,460.6,468.8
XS GIS Cut Line= 3
     1973743.098      125657.892     1973559.965      125291.624
     1973375.898      124925.823
#Sta/Elev= 30
       0 2023.58    69.9 2001.11    89.9 1997.28   129.8 1972.17   139.8 1967.68
   149.8 1964.85   179.8 1959.19   189.8 1958.94   269.7 1942.62   336.6 1935.12
   339.6 1934.81   351.6 1935.82   379.5 1945.08   389.5 1946.97   399.5 1946.72
   409.5 1948.16   439.5  1954.5   459.4 1961.25   489.4 1973.85   499.4 1974.56
   509.4 1978.71   559.3 2007.21   589.3 2022.04   599.3 2023.69   609.3  2023.8
   689.2 2021.36   739.1 2023.96   749.1 2025.79     809 2054.92     819 2057.49
#Mann= 3 , 0 , 0
       0     .08       0   336.6    .045       0   351.6     .08       0
Bank Sta=336.6,351.6
XS Rating Curve= 0 ,0
Exp/Cntr=0.3,0.1

Type RM Length L Ch R = 1 ,2682.1  ,288,287.8,287.6
XS GIS Cut Line= 2
     1974080.486      125654.794     1974016.476      125041.365
#Sta/Elev= 30
       0 2040.95    19.9 2034.77    59.7 2020.83    79.6 2017.55    89.5 2013.78
    99.5 2008.29   119.4 1995.43   149.2 1980.99   159.2 1977.52   169.1  1976.3
   179.1 1972.56   218.8 1960.82   228.8 1957.68   258.6 1945.85   268.6 1945.01
   288.5 1937.06   305.8 1931.95   318.3 1929.16   320.8 1929.18   328.3 1929.26
   348.2 1931.66   368.1 1933.01   447.6 1947.91   457.6    1948   467.5 1949.69
   477.5 1952.46   537.2 1979.62   547.1 1980.12   557.1 1984.24   616.8 2013.59
#Mann= 3 , 0 , 0
       0     .08       0   305.8    .045       0   320.8     .08       0
Bank Sta=305.8,320.8
XS Rating Curve= 0 ,0
Exp/Cntr=0.3,0.1

Type RM Length L Ch R = 1 ,2394.3  ,408.3,436.8,465.3
XS GIS Cut Line= 2
     1974361.946      125602.702     1974286.934      124960.603
#Sta/Elev= 30
       0  1998.6      10 1996.06    19.9 1995.42    29.8 1993.61    49.7 1983.81
    59.7 1980.21    79.6 1974.97    99.5 1971.11   119.4 1969.58   129.3 1967.97
   149.2 1963.56   169.1 1956.21   198.9 1943.05   248.6 1934.78   308.3 1933.88
   318.3 1931.53   338.2 1924.98   343.8 1924.05   348.1 1923.34   358.8 1924.29
   387.9 1933.04   397.8 1935.38   407.8 1935.97   417.7    1939   457.5 1953.16
   487.3 1966.52   497.3 1966.81   586.8 2009.72   596.7 2009.96   646.5 2033.69
#Mann= 3 , 0 , 0
       0     .08       0   343.8    .045       0   358.8     .08       0
Bank Sta=343.8,358.8
XS Rating Curve= 0 ,0
Exp/Cntr=0.3,0.1

Type RM Length L Ch R = 1 ,1957.5  ,187.2,196.3,205.5
XS GIS Cut Line= 3
     1974445.805      125496.483     1974937.414      125258.782
     1974950.019      124986.866
#Sta/Elev= 30
       0 1947.09     9.9 1944.25    29.8 1936.62    99.3 1925.84   119.1 1924.81
   188.6 1923.86   228.4 1922.59   268.1 1921.22   288.6 1919.52   303.6 1917.02
   307.8 1916.44   317.7 1918.07   327.6 1924.81   347.5 1946.97   357.4 1955.77
   367.4 1962.53   397.1 1974.52   407.1 1976.89   436.8 1981.23   466.6 1983.12
   516.3 1984.47   575.2 1987.78     653 1991.08   711.3 1992.55   750.2 1995.09
   759.9 1996.64   779.4 2002.78   789.1 2005.08   798.8 2006.16   818.3 2012.08
#Mann= 3 , 0 , 0
       0      .1       0   288.6    .045       0   303.6      .1       0
Bank Sta=288.6,303.6
XS Rating Curve= 0 ,0
Exp/Cntr=0.3,0.1

Type RM Length L Ch R = 1 ,1761.5  ,427.5,410.8,394.1
XS GIS Cut Line= 2
     1974430.957      125572.698      1974965.04      125545.694
#Sta/Elev= 30
       0 1966.56    29.7 1960.15    39.6 1953.46    69.3 1939.96    79.2 1936.35
    89.1 1933.62   108.9 1929.54   118.8  1926.4   138.6  1924.1   188.2 1919.75
   198.1 1918.17   217.9 1917.71   227.8 1916.91   237.7  1914.6   247.6 1911.05
   257.9  1908.4   267.4 1908.13   272.9 1909.19   277.3 1910.03   287.2 1917.96
   297.1 1922.89   336.7 1939.84   346.6 1943.61   366.4 1948.34   386.2 1950.01
   415.9  1950.3   435.7 1951.01   455.5 1953.02   495.2 1955.78   534.8 1956.81
#Mann= 3 , 0 , 0
       0      .1       0   257.9    .045       0   272.9      .1       0
Bank Sta=257.9,272.9
XS Rating Curve= 0 ,0
Exp/Cntr=0.3,0.1

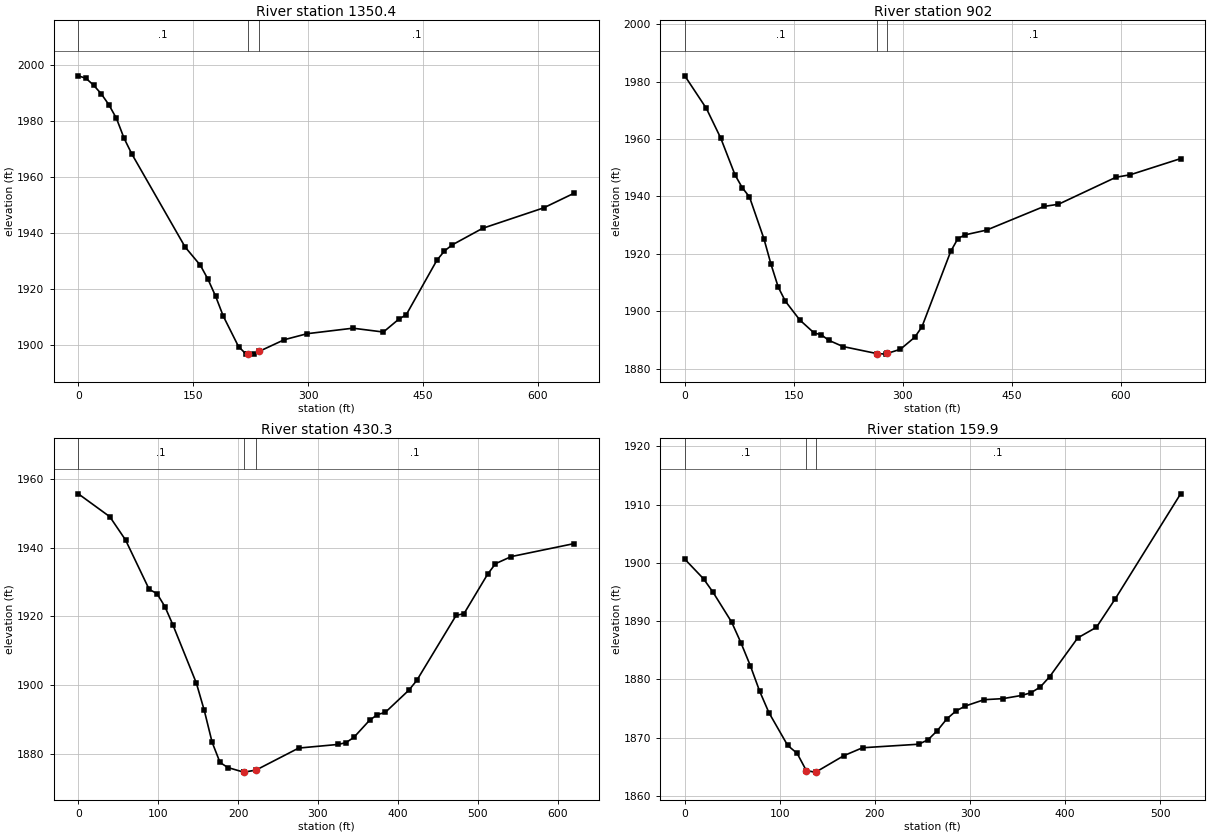
Type RM Length L Ch R = 1 ,1350.4  ,456.1,448.3,440.5
XS GIS Cut Line= 2
      1974583.98      126078.276     1975047.552      125626.706
#Sta/Elev= 30
       0  1996.1      10 1995.21    19.9 1992.77    29.9 1989.69    39.8 1985.81
    49.8  1980.9    59.7 1973.84    69.7 1968.29   139.4 1935.04   159.3 1928.53
   169.3 1923.51   179.2 1917.49   189.2  1910.4   209.1 1899.54     219 1896.85
   221.2 1896.86     229 1896.89   236.2 1897.85   268.8 1901.99   298.7 1904.14
   358.4  1906.1   398.2 1904.73   418.2 1909.29   428.1 1910.93     468 1930.32
   477.9 1933.64   487.9 1935.79   527.7 1941.72   607.3    1949   647.2 1954.25
#Mann= 3 , 0 , 0
       0      .1       0   221.2    .045       0   236.2      .1       0
Bank Sta=221.2,236.2
XS Rating Curve= 0 ,0
Exp/Cntr=0.3,0.1

Type RM Length L Ch R = 1 ,902     ,484.2,471.7,459.3
XS GIS Cut Line= 2
     1974981.542       126426.33      1975286.09      125815.736
#Sta/Elev= 30
       0    1982    29.7 1970.63    49.4 1960.33    69.2 1947.42    79.1    1943
      89 1939.79   108.8 1925.29   118.7 1916.27   128.6 1908.34   138.4 1903.45
   158.2 1896.92     178 1892.37   187.9 1891.75   197.8 1889.87   217.6 1887.66
   263.9 1885.22   276.9 1885.01   278.9 1885.27   296.7 1886.71   316.4 1890.89
   326.3 1894.51   365.9 1920.81   375.8 1925.27   385.7 1926.58   415.3 1928.24
   494.4 1936.49   514.2 1937.24   593.3 1946.65   613.1 1947.53   682.3 1953.15
#Mann= 3 , 0 , 0
       0      .1       0   263.9    .045       0   278.9      .1       0
Bank Sta=263.9,278.9
XS Rating Curve= 0 ,0
Exp/Cntr=0.3,0.1

Type RM Length L Ch R = 1 ,430.3   ,258.6,270.4,282.2
XS GIS Cut Line= 2
     1975574.134      126450.334     1975535.128      125830.738
#Sta/Elev= 30
       0 1955.71    39.4 1949.04    59.1 1942.27    88.7 1927.87    98.5 1926.63
   108.4 1922.84   118.2 1917.63   147.8 1900.54   157.7 1892.58   167.5 1883.32
   177.4 1877.42   187.2 1875.95   206.9 1874.61   207.4 1874.61   222.4  1875.2
   275.9 1881.62   325.2 1882.68     335 1883.19   344.9 1884.72   364.6 1889.71
   374.5 1891.37   384.3 1892.02   413.9 1898.51   423.7 1901.32     473 1920.28
   482.9  1920.8   512.4 1932.27   522.3 1935.35     542 1937.42   620.8 1941.21
#Mann= 3 , 0 , 0
       0      .1       0   207.4    .045       0   222.4      .1       0
Bank Sta=207.4,222.4
XS Rating Curve= 0 ,0
Exp/Cntr=0.3,0.1

Type RM Length L Ch R = 1 ,159.9   ,159.2,159.9,160.6
XS GIS Cut Line= 2
      1975749.39      126453.983     1975979.325      125986.009
#Sta/Elev= 30
       0 1900.63    19.7 1897.26    29.5    1895    49.2 1889.85      59  1886.3
    68.9 1882.36    78.7 1877.98    88.5 1874.28   108.2 1868.67   118.1 1867.32
   127.9 1864.32   137.7 1864.09   167.2 1866.91   186.9 1868.27     246 1868.88
   255.8 1869.64   265.6 1871.22   275.5 1873.22   285.3  1874.6   295.1 1875.44
   314.8 1876.52   334.5  1876.7   354.2 1877.25     364 1877.71   373.8 1878.69
   383.7 1880.47   413.2 1887.12   432.9 1888.95   452.6 1893.81   521.4 1911.84
#Mann= 3 , 0 , 0
       0      .1       0   127.9    .045       0   137.7      .1       0
Bank Sta=127.9,137.7
XS Rating Curve= 0 ,0
Exp/Cntr=0.3,0.1

Chan Stop Cuts=-1
Use User Specified Reach Order=0
Composite Channel Slope=5